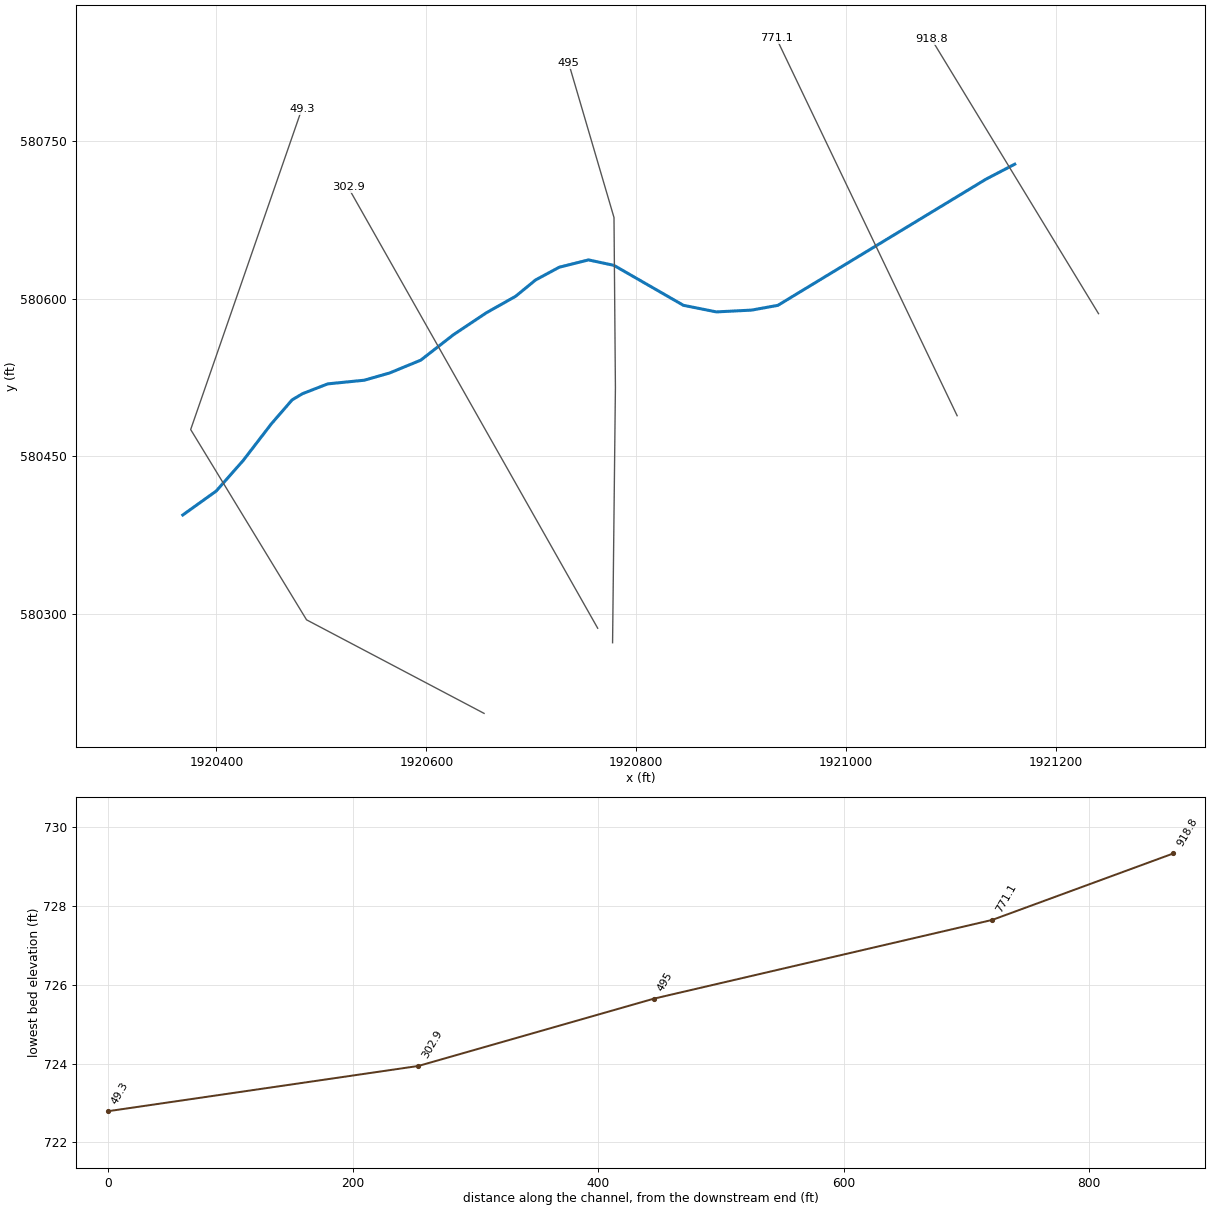
--- BlwnTmbrRn.prj (project) ---

Proj Title=BlwnTmbrRn
Current Plan=p01
Default Exp/Contr=0,0
English Units
Geom File=g01
Flow File=f01
Plan File=p01
BEGIN DESCRIPTION:
AMEC Environment & Infrastructure, 2013
Projection: NAD 1983 State Plane West Virginia South FIPS 4702 (US Feet)
Vertical Datum: NAVD 1988
END DESCRIPTION:
DSS Export Rating Curves= 0
DSS Export Rating Curve Sorted= 0
DSS Export Volume Flow Curves= 0
DXF OffsetX= 0
DXF OffsetY= 0
DXF ScaleX= 0
DXF ScaleY= 0

--- BlwnTmbrRn.p01 (plan) ---

Plan Title=Floodplain
Program Version=4.00
Geom File=g01
Flow File=f01
K Sum by GR=0
Std Step Tol=0.01
Critical Tol=0.01
Num of Std Step Trials=20
Max Error Tol=0.3
Flow Tol Ratio=0.001
Split Flow NTrial=30
Split Flow Tol=0.02
Split Flow Ratio=0.02
Log Output Level=0
Friction Slope Method=1
Unsteady Friction Slope Method=2
Unsteady Bridges Friction Slope Method=1
Global Log Level=0
CheckData=False
Run HTab=0
Run UNet=0
Run PostProcess=0
UNET Theta=0
UNET Theta Warmup=0
UNET ZTol=0
UNET ZSATol=0
UNET MxIter=0
UNET MaxInSteps=0
UNET DtIC=0
UNET DtMin=0
UNET MaxCRTS=0
UNET WFStab=0
UNET SFStab=0
UNET WFX=0
UNET SFX=0
UNET DSS MLevel=0
UNET DZMax Abort=0
UNET Convert EG Bridges=0
UNET Use Existing IB Tables=0
UNET Froude Limit=0
UNET Froude Power=0
Write IC File=0
Echo Input=False
Echo Output=False
Write Detailed=0

--- BlwnTmbrRn.f01 (steady flow) ---

Flow Title=NFF Regression Equation
Program Version=4.10
Number of Profiles= 1
Profile Names=P100yr
River Rch & RM=BlwnTmbrRn,Main            ,918.8
 899.617
Boundary for River Rch & Prof#=BlwnTmbrRn,Main            , 1
Up Type= 0
Dn Type= 3
Dn Slope=0.006908
DSS Import GetInterval= 0
DSS Import GetPeak= 0
DSS Import FillOption= 0

--- BlwnTmbrRn.g01 (geometry) ---

Geom Title=USGS 3m DEM
Program Version=4.10

River Reach=BlwnTmbrRn      ,Main
Reach XY= 23
     1921160.454      580728.314      1921133.11      580714.072
     1920934.866      580593.873     1920909.801      580589.316
     1920876.191      580587.607     1920844.859      580593.873
     1920778.675      580631.933     1920754.361      580637.143
     1920726.573      580630.195     1920703.996      580618.038
     1920684.893      580602.407     1920657.105      580586.777
     1920625.845      580565.935     1920594.585      580541.621
     1920565.061      580529.463     1920540.747      580522.516
     1920506.012      580519.042     1920481.943      580509.682
     1920472.073      580503.794     1920452.175      580480.834
     1920425.475      580446.099     1920399.744      580416.937
     1920367.923       580394.14

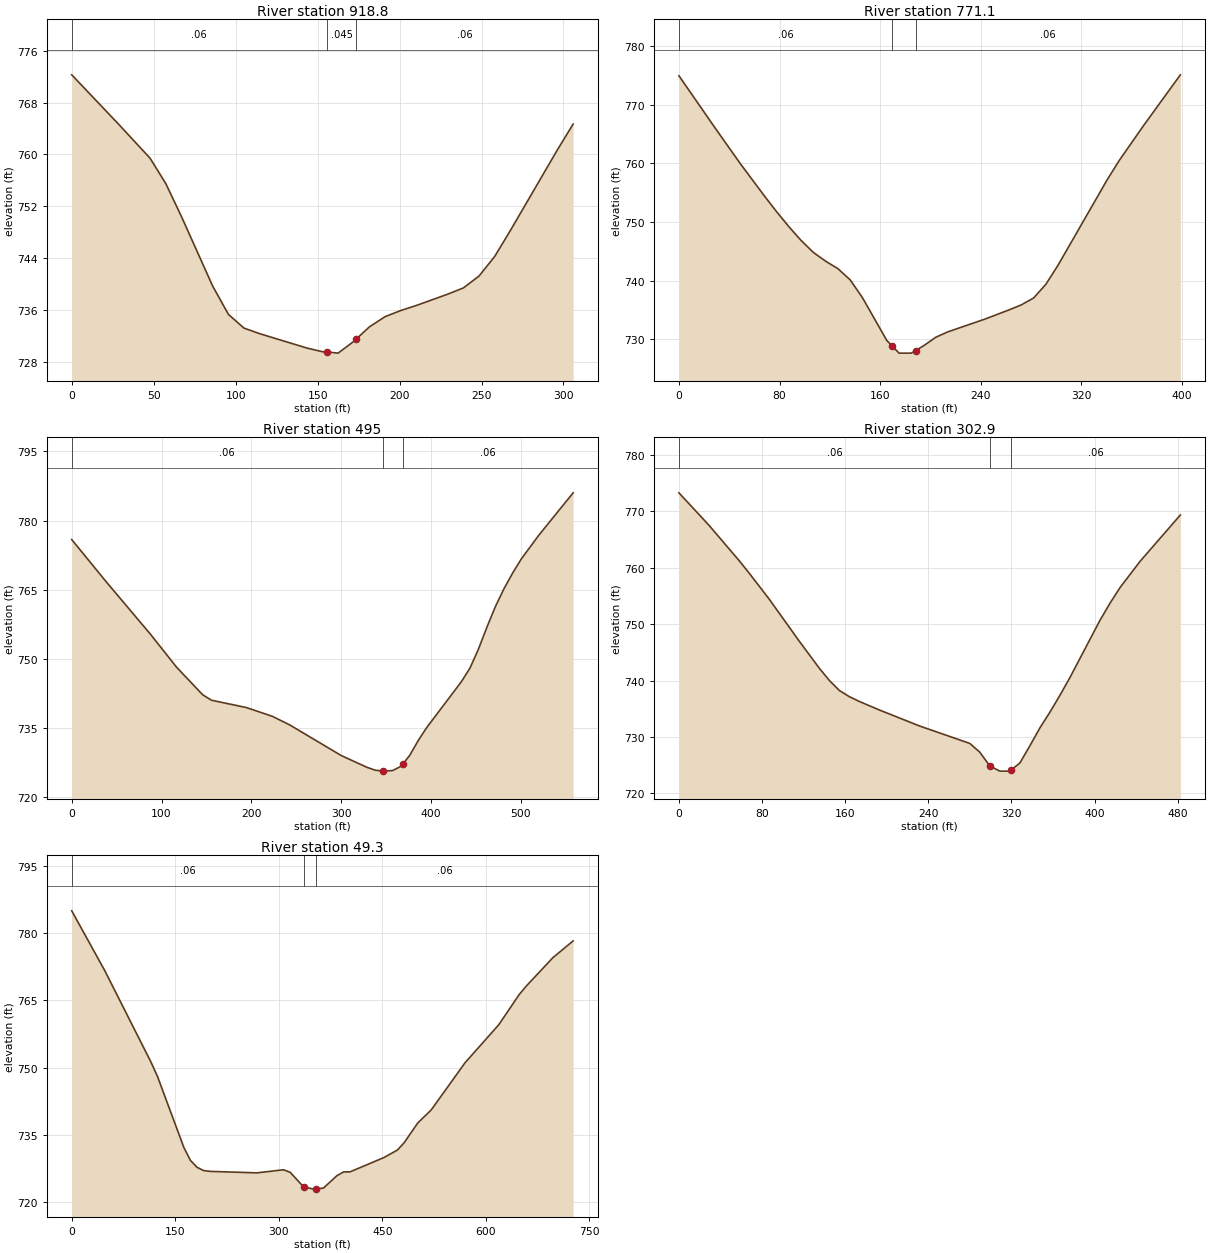
Type RM Length L Ch R = 1 ,918.8   ,150.3,147.8,145.3
XS GIS Cut Line= 2
     1921240.302      580585.929     1921081.302      580847.216
#Sta/Elev= 26
       0  772.29    28.7  764.64    47.8  759.42    57.4   755.5    66.9  750.44
      86  739.68    95.6  735.32   105.1   733.2   114.7  732.34   143.4  730.13
   152.9  729.56  155.64  729.53   162.5  729.34     172  731.14   173.5  731.49
   181.6  733.39   191.2  734.97   200.7  735.91   210.3   736.7   229.4  738.44
     239  739.41   248.5  741.24   258.1  744.28   267.6  748.26   296.3  760.71
   305.9  764.69
#Mann= 3 , 0 , 0
       0     .06       0  155.64    .045       0   173.5     .06       0
Bank Sta=155.64,173.5
XS Rating Curve= 0 ,0
Exp/Cntr=0.3,0.1

Type RM Length L Ch R = 1 ,771.1   ,285.7,275.9,264.8
XS GIS Cut Line= 2
     1921105.607      580488.706     1920933.442      580848.228
#Sta/Elev= 30
       0  774.95    29.2  765.91    48.6  760.02    68.1  754.41    77.8  751.73
    87.5  749.19    97.2  746.84     107   744.8   116.7  743.32   126.4  742.05
   136.1  740.15   145.8  737.14   165.3  729.79   169.3  728.91     175  727.65
   184.7  727.65  188.16  728.09   194.4  728.89   204.2  730.36   213.9  731.29
   243.1  733.44   262.5  735.03   272.2  735.88     282  737.06   291.7  739.39
   301.4  742.65   340.3  757.16     350   760.5   369.4  766.46   398.6  775.11
#Mann= 3 , 0 , 0
       0     .06       0   169.3    .045       0  188.16     .06       0
Bank Sta=169.3,188.16
XS Rating Curve= 0 ,0
Exp/Cntr=0.3,0.1

Type RM Length L Ch R = 1 ,495     ,180.6,192.1,204.9
XS GIS Cut Line= 4
     1920777.354      580272.424     1920780.054      580515.481
     1920778.704      580677.519     1920735.494      580824.703
#Sta/Elev= 30
       0  775.87    38.9   766.6    87.5  755.39   116.7  748.21   145.8  742.22
   155.6  741.03   194.5  739.44   223.6  737.53   243.1  735.64   300.3  729.02
   328.9  726.47   338.4  725.84  346.38  725.68   347.9  725.65   357.5  725.78
     367  726.72   369.3  727.29   376.5  729.08     386   732.3   395.6  735.15
   433.9  745.02   443.5  747.96     453   752.1   462.6  756.94   472.2  761.47
   481.8  765.33   491.4  768.71     501  771.73   520.2   776.8   558.5  786.01
#Mann= 3 , 0 , 0
       0     .06       0  346.38    .045       0   369.3     .06       0
Bank Sta=346.38,369.3
XS Rating Curve= 0 ,0
Exp/Cntr=0.3,0.1

Type RM Length L Ch R = 1 ,302.9   ,252.5,253.2,253.9
XS GIS Cut Line= 2
     1920763.175      580286.264      1920525.52      580706.213
#Sta/Elev= 30
       0  773.27      29   767.5    57.9  761.26    67.6  759.03    86.9  754.42
   115.8  746.97   135.1  742.18   144.8     740   154.4  738.23   164.1  737.13
   173.7  736.28     193  734.77   231.6  731.94   279.9  728.85   289.5   727.3
   299.2  724.85   308.8  723.94   318.4  723.94  319.42   724.1   328.1  725.38
   337.8  728.46   347.4  731.62   357.1  734.42   366.7   737.4   376.4  740.58
   405.3  750.72     415  753.76   424.6  756.51   443.9  761.16   482.5  769.34
#Mann= 3 , 0 , 0
       0     .06       0   299.2    .045       0  319.42     .06       0
Bank Sta=299.2,319.42
XS Rating Curve= 0 ,0
Exp/Cntr=0.3,0.1

Type RM Length L Ch R = 1 ,49.3    ,47.3,49.4,51.5
XS GIS Cut Line= 4
     1920654.939       580205.14     1920485.812      580294.261
     1920375.423      580475.541      1920481.29      580780.787
#Sta/Elev= 30
       0  785.06    47.8   771.7   114.7  751.25   124.3  747.99   162.5   732.1
     172  729.22   181.6  727.67   191.2  726.94   200.8  726.76   268.4  726.43
   306.9  727.12   316.6  726.54   335.9   723.3  350.64  722.79   353.7   722.8
   364.8  723.03   384.1  725.78   393.8  726.64   403.4  726.66   452.4  729.86
     472  731.55   481.7  733.18   501.3  737.58   520.9  740.52   569.8  751.05
   618.8  759.58   648.2  766.29     658  768.12   697.1  774.57   726.5  778.33
#Mann= 3 , 0 , 0
       0     .06       0   335.9    .045       0   353.7     .06       0
Bank Sta=335.9,353.7
XS Rating Curve= 0 ,0
Exp/Cntr=0.3,0.1

Chan Stop Cuts=-1
Use User Specified Reach Order=0
Composite Channel Slope=5